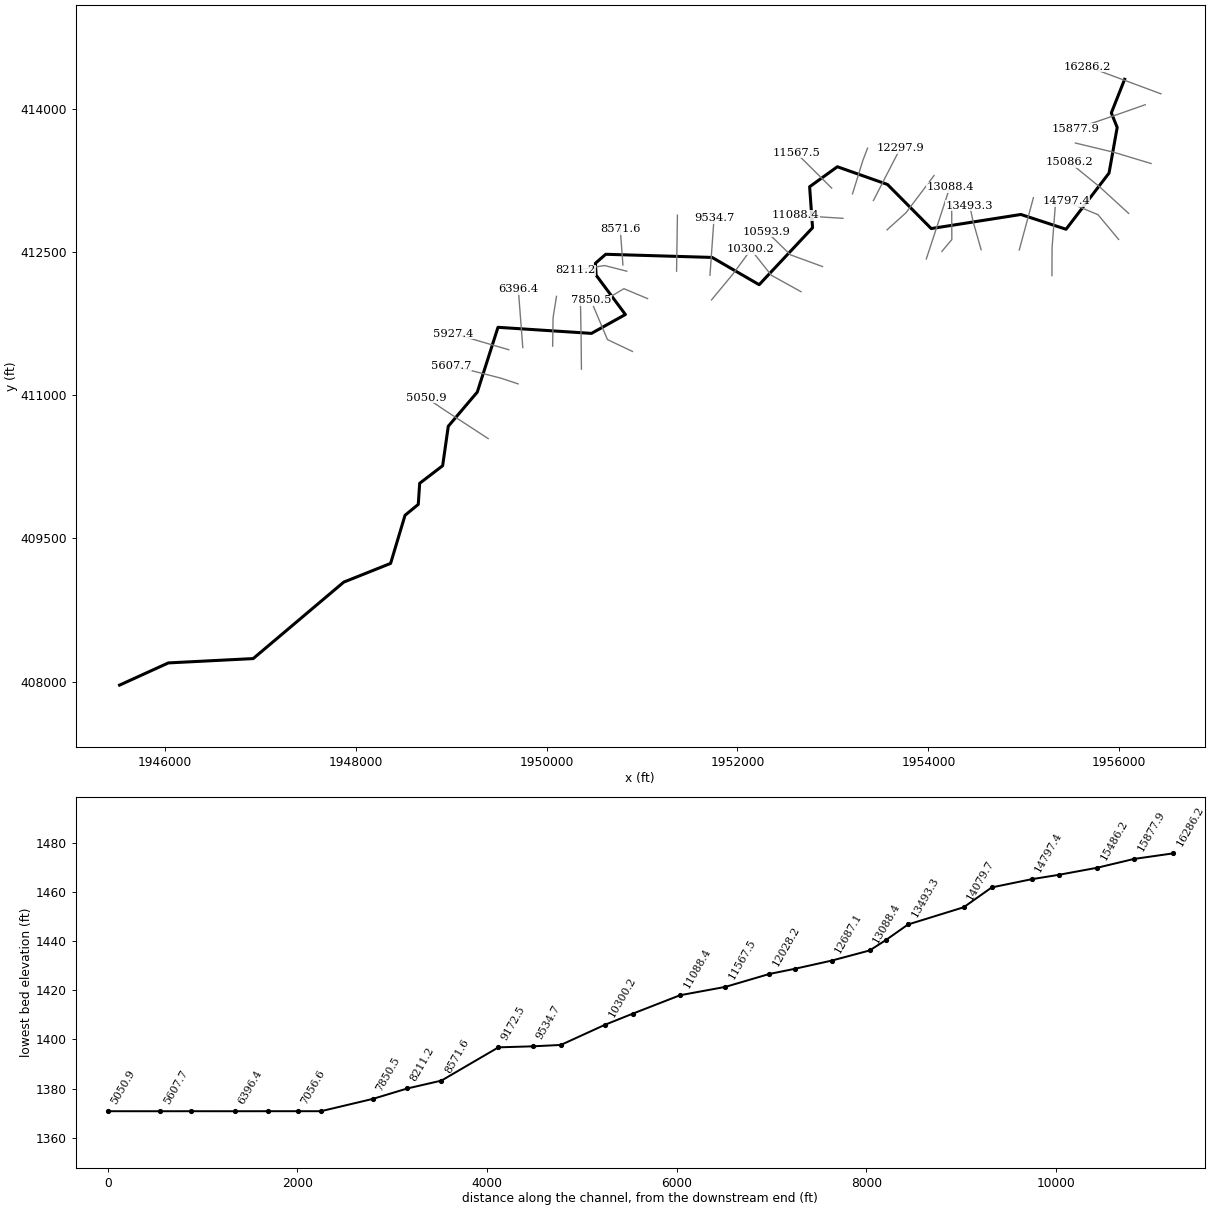
--- OsbrneCrk.prj (project) ---

Proj Title=OsbrneCrk
Current Plan=p01
Default Exp/Contr=0,0
English Units
Geom File=g01
Flow File=f01
Plan File=p01
BEGIN DESCRIPTION:
END DESCRIPTION:
DSS Export Rating Curves= 0
DSS Export Rating Curve Sorted= 0
DSS Export Volume Flow Curves= 0
DXF OffsetX= 0
DXF OffsetY= 0
DXF ScaleX= 0
DXF ScaleY= 0

--- OsbrneCrk.p01 (plan) ---

Plan Title=Floodplain
Program Version=4.00
Geom File=g01
Flow File=f01
K Sum by GR=0
Std Step Tol=0.01
Critical Tol=0.01
Num of Std Step Trials=20
Max Error Tol=0.3
Flow Tol Ratio=0.001
Split Flow NTrial=30
Split Flow Tol=0.02
Split Flow Ratio=0.02
Log Output Level=0
Friction Slope Method=1
Unsteady Friction Slope Method=2
Unsteady Bridges Friction Slope Method=1
Global Log Level=0
CheckData=False
Run HTab=0
Run UNet=0
Run PostProcess=0
UNET Theta=0
UNET Theta Warmup=0
UNET ZTol=0
UNET ZSATol=0
UNET MxIter=0
UNET MaxInSteps=0
UNET DtIC=0
UNET DtMin=0
UNET MaxCRTS=0
UNET WFStab=0
UNET SFStab=0
UNET WFX=0
UNET SFX=0
UNET DSS MLevel=0
UNET DZMax Abort=0
UNET Convert EG Bridges=0
UNET Use Existing IB Tables=0
UNET Froude Limit=0
UNET Froude Power=0
Write IC File=0
Echo Input=False
Echo Output=False
Write Detailed=0

--- OsbrneCrk.f01 (steady flow) ---

Flow Title=NFF Regression Equation
Program Version=4.00
Number of Profiles=1
Profile Names=P100yr
River Rch & RM=OsbrneCrk,Main      ,16286.2
502.4933
River Rch & RM=OsbrneCrk,Main      ,14375.9
820.5071
River Rch & RM=OsbrneCrk,Main      ,14375.9
546.3167
River Rch & RM=OsbrneCrk,Main      ,12297.9
899.8854
River Rch & RM=OsbrneCrk,Main      ,11567.5
996.6061
River Rch & RM=OsbrneCrk,Main      ,9534.7
1016.622
River Rch & RM=OsbrneCrk,Main      ,3712.7
1127.742
River Rch & RM=OsbrneCrk,Main      ,2983.2
1304.554
River Rch & RM=OsbrneCrk,Main      ,244.4
1339.967
Boundary for River Rch & Prof#=OsbrneCrk,Main      ,1
Up Type=0
Dn Type=3
Dn Slope=0.019254

--- OsbrneCrk.g01 (geometry) ---

Geom Title=USGS 3m DEM
Program Version=4.10

River Reach=OsbrneCrk       ,Main
Reach XY= 30
     1956055.541      414306.668     1955916.209      413955.156
     1955977.463      413802.914      1955892.14      413325.353
     1955441.881      412737.192     1954968.735      412891.737
     1954029.499      412744.167     1953571.166      413205.973
     1953046.214      413391.333     1952755.655      413181.988
     1952786.443      412752.848     1952226.827      412156.523
      1951734.36      412442.084     1950619.777       412475.07
     1950511.579      412380.734     1950519.082       412256.32
     1950825.778      411844.646     1950470.471      411646.945
     1949491.175      411710.516     1949274.291      411032.362
     1948970.471      410674.723     1948911.444      410261.529
     1948670.892      410077.553     1948656.235      409857.015
     1948517.346      409742.431     1948366.305      409238.959
     1947875.504      409043.188     1946926.777      408242.613
      1946038.18      408197.293     1945527.036      407964.798

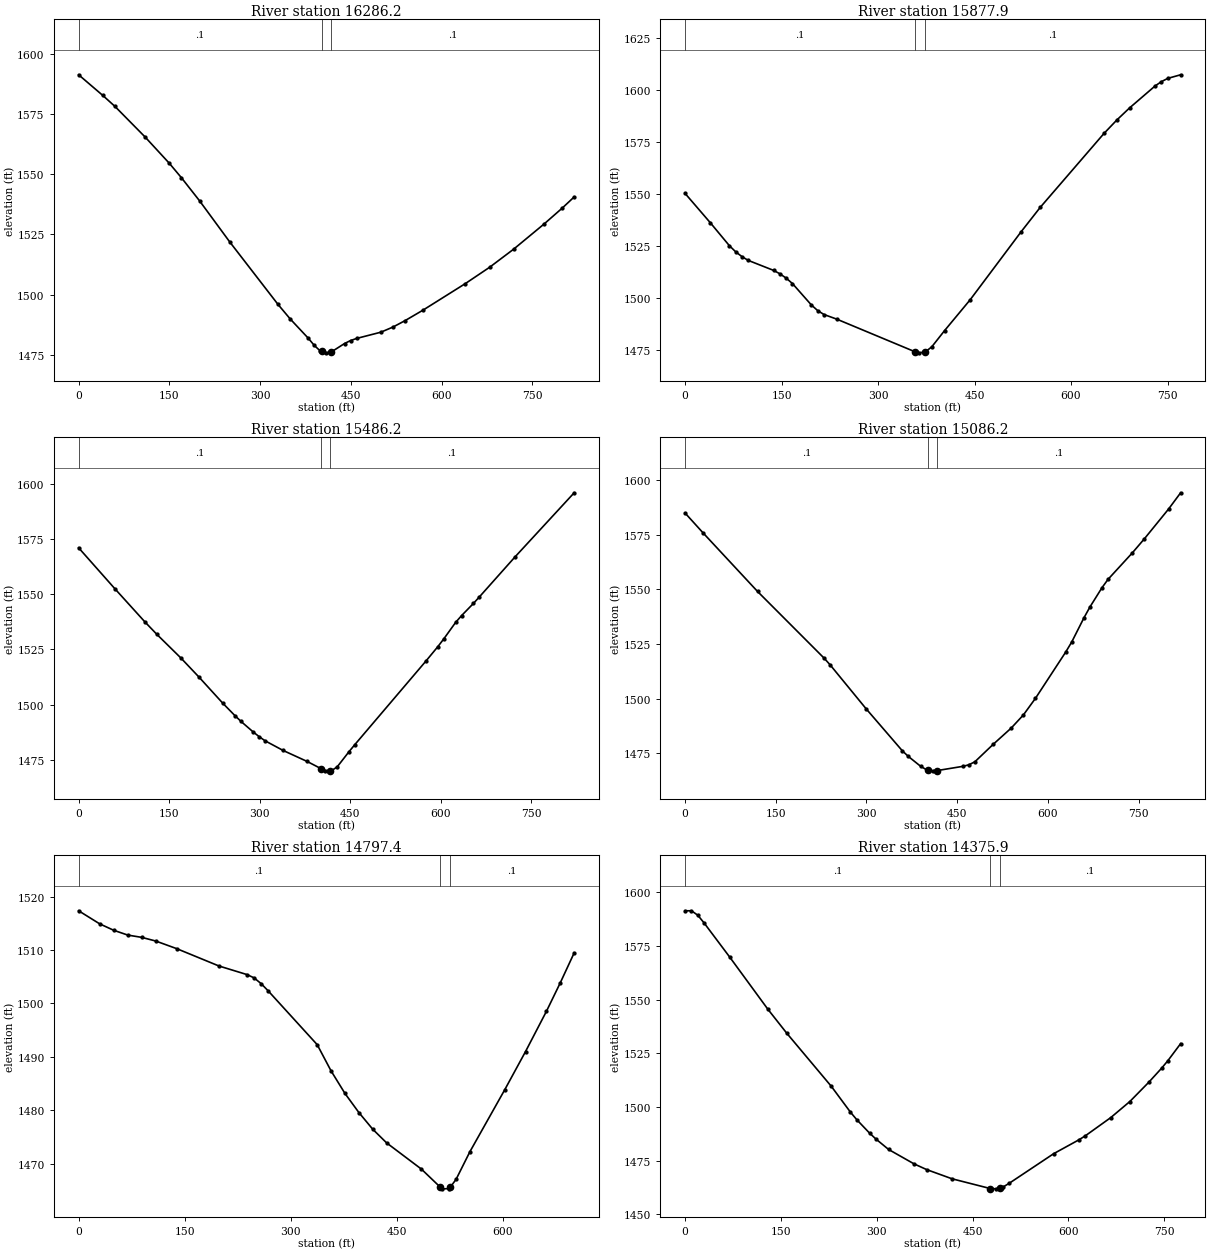
Type RM Length L Ch R = 1 ,16286.2 ,392.5,408.1,423.8
XS GIS Cut Line= 3
     1956435.935      414154.713     1956052.059      414297.293
     1955668.182      414439.874
#Sta/Elev= 30
       0  1591.3      40  1582.7    59.9 1578.19   109.9 1565.44   149.8 1554.55
   169.8 1548.56   199.8 1538.96   249.7 1521.87   329.6 1495.87   349.6 1489.88
   379.5 1481.86   389.5 1478.86   399.5 1476.52     402 1476.34   409.5 1475.78
     417 1476.28   419.5 1476.45   439.5 1479.65   449.4 1480.88   459.4 1481.76
   499.4 1484.35   519.4 1486.48   539.3 1489.13   569.3 1493.54   639.2 1504.56
   679.2 1511.32   719.1 1518.88   769.1 1529.27     799 1535.85     819 1540.55
#Mann= 3 , 0 , 0
       0      .1       0     402    .045       0     417      .1       0
Bank Sta=402,417
XS Rating Curve= 0 ,0
Exp/Cntr=0.3,0.1

Type RM Length L Ch R = 1 ,15877.9 ,405.8,391.7,378.8
XS GIS Cut Line= 3
     1956270.955       414040.71     1955974.519      413936.436
     1955543.031      413788.541
#Sta/Elev= 30
       0 1550.12    39.3 1536.01    68.7 1525.07    78.6 1522.09    88.4 1519.76
    98.2 1517.95   137.5 1513.16   147.3 1511.53   157.1 1509.44   166.9 1506.83
   196.4 1496.51   206.2 1493.82     216 1491.94   235.7 1489.74   357.3 1474.07
   363.8 1473.54   372.3 1473.95   373.7 1474.02   383.6 1476.47   403.5 1484.26
   443.2 1499.04   522.5 1531.75   552.2 1543.46   651.4    1579   671.2  1585.4
     691 1591.21   730.7 1601.76   740.6 1603.85   750.5 1605.41   770.4 1607.13
#Mann= 3 , 0 , 0
       0      .1       0   357.3    .045       0   372.3      .1       0
Bank Sta=357.3,372.3
XS Rating Curve= 0 ,0
Exp/Cntr=0.3,0.1

Type RM Length L Ch R = 1 ,15486.2 ,410.1,400,389.9
XS GIS Cut Line= 3
     1956332.451      413425.015     1955940.914      413543.133
     1955539.756      413639.637
#Sta/Elev= 30
       0 1571.13    59.8 1552.65   109.7 1537.57   129.7 1531.86   169.6 1521.12
   199.5 1512.48   239.4  1500.5   259.3 1494.94   269.3 1492.34   289.3  1487.6
   299.2 1485.46   309.2 1483.55   339.1 1479.17     379 1474.17   401.5 1470.98
     409 1470.06   416.5 1469.96   418.8 1469.93   428.6  1471.7   448.3 1478.63
   458.1 1481.88     576  1519.8   595.6 1526.29   605.4 1529.79   625.1  1537.3
   634.9 1540.36   654.6  1545.9   664.4 1548.84   723.3 1566.93   821.6  1596.1
#Mann= 3 , 0 , 0
       0      .1       0   401.5    .045       0   416.5      .1       0
Bank Sta=401.5,416.5
XS Rating Curve= 0 ,0
Exp/Cntr=0.3,0.1

Type RM Length L Ch R = 1 ,15086.2 ,280.9,288.7,295.3
XS GIS Cut Line= 3
     1956097.205      412903.149     1955795.182      413179.469
     1955477.024      413438.585
#Sta/Elev= 30
       0 1584.82      30 1575.68   119.8 1549.02   229.6 1518.64   239.6 1515.59
   299.5  1495.4   359.4 1476.21   369.4 1473.63   389.4  1469.2   399.4 1467.56
   401.9 1467.44   409.4 1467.08   416.9  1467.2   459.4 1469.13   469.4 1469.83
   479.4 1471.23   509.4 1479.13   539.5 1486.63   559.5 1492.58   579.5 1500.18
   629.5 1521.29   639.5  1525.9   659.6 1536.88   669.6 1541.89   689.6 1550.73
   699.6 1554.54   739.6 1566.57   759.6 1573.02   799.7 1586.64   819.7 1594.08
#Mann= 3 , 0 , 0
       0      .1       0   401.9    .045       0   416.9      .1       0
Bank Sta=401.9,416.9
XS Rating Curve= 0 ,0
Exp/Cntr=0.3,0.1

Type RM Length L Ch R = 1 ,14797.4 ,449.7,421.5,393.2
XS GIS Cut Line= 3
     1955992.643      412630.279     1955776.647      412889.475
     1955441.232      413029.252
#Sta/Elev= 30
       0 1517.34    29.8 1514.89    49.6 1513.69    69.5 1512.79    89.3 1512.36
   109.2 1511.67   138.9 1510.24   198.5    1507   238.2 1505.39   248.1 1504.78
     258 1503.71   267.9 1502.37   337.4 1492.27     357 1487.36   376.7 1483.13
   396.3 1479.57     416 1476.43   435.6 1473.88   484.7 1468.98   510.7 1465.69
   514.2 1465.28     524 1465.31   525.7 1465.61   533.8 1467.06   553.5 1472.27
   602.6 1483.83     632 1490.98   661.5  1498.5   681.1 1503.84   700.8 1509.46
#Mann= 3 , 0 , 0
       0      .1       0   510.7    .045       0   525.7      .1       0
Bank Sta=510.7,525.7
XS Rating Curve= 0 ,0
Exp/Cntr=0.3,0.1

Type RM Length L Ch R = 1 ,14375.9 ,300.5,296.1,291.7
XS GIS Cut Line= 3
     1955294.007      412251.914     1955295.248      412540.653
     1955332.489      413026.273
#Sta/Elev= 30
       0 1591.43      10 1591.43    19.9 1589.35    29.9  1585.7    69.7 1569.92
   129.4 1545.65   159.3 1534.36     229 1509.64   258.9 1497.63   268.8 1494.13
   288.7 1487.91   298.7 1485.14   318.6 1480.27   358.3 1473.58   378.2 1470.89
     418  1466.6   477.9 1462.06   487.5 1461.93   492.9 1462.36   497.5 1462.73
   507.4 1464.51     577  1478.3   616.8  1484.8   626.7 1486.65   666.4 1495.11
   696.3  1502.6   726.1 1511.62     746 1518.11   755.9 1521.65   775.8 1529.56
#Mann= 3 , 0 , 0
       0      .1       0   477.9    .045       0   492.9      .1       0
Bank Sta=477.9,492.9
XS Rating Curve= 0 ,0
Exp/Cntr=0.3,0.1

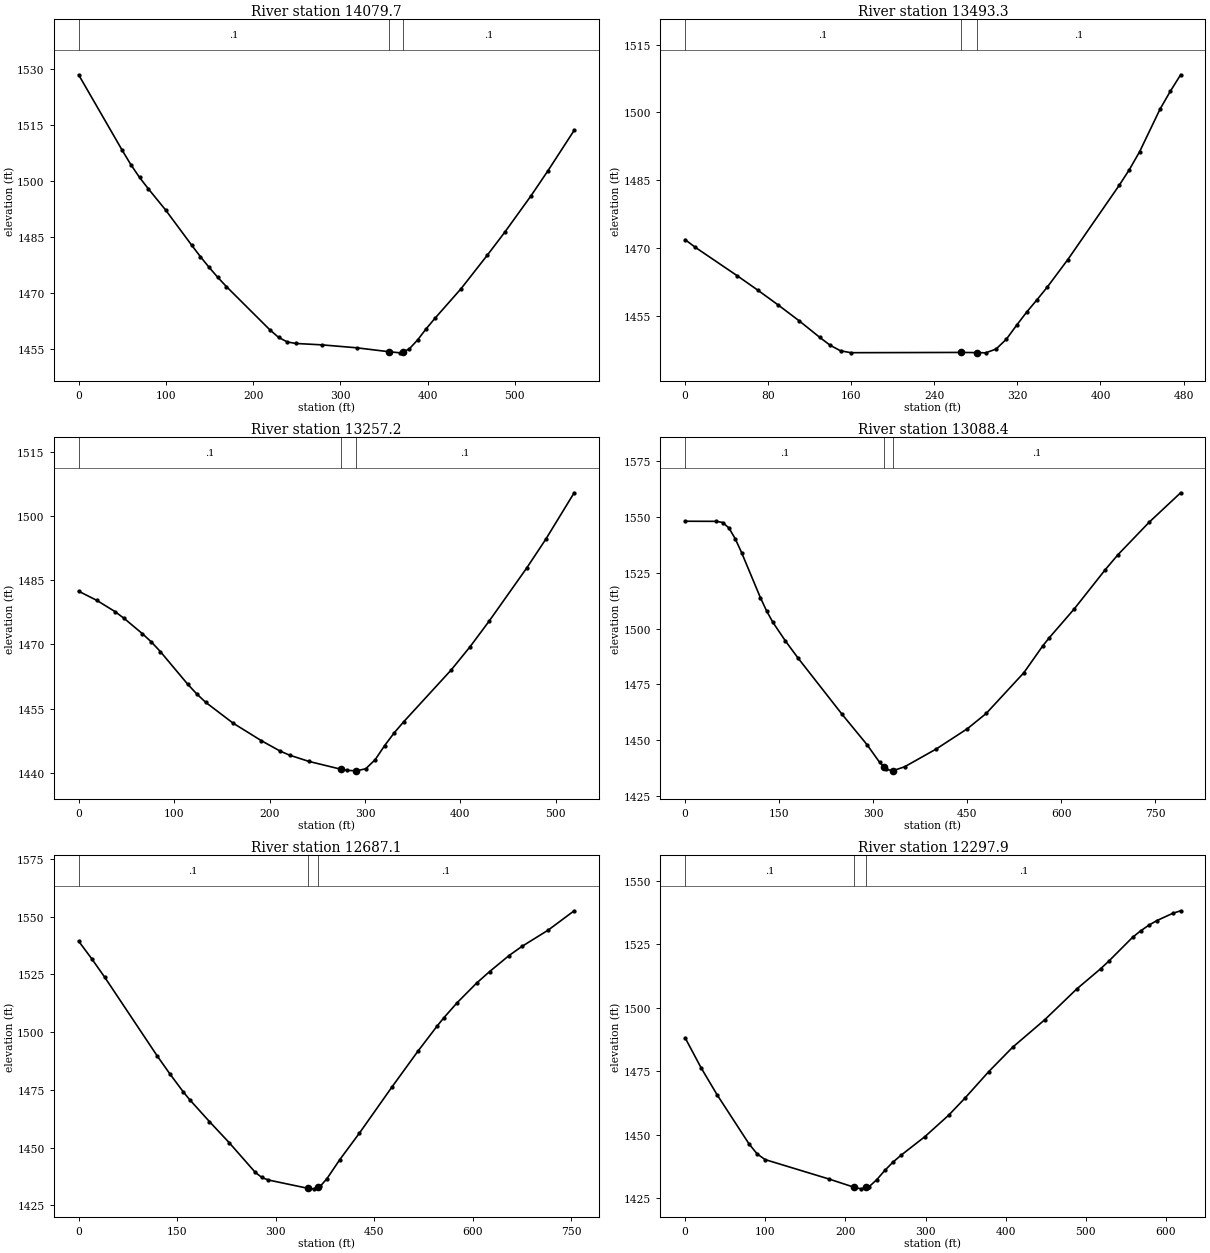
Type RM Length L Ch R = 1 ,14079.7 ,574,586.4,598.7
XS GIS Cut Line= 2
     1954951.392      412519.799     1955100.107      413067.982
#Sta/Elev= 30
       0 1528.53    49.8 1508.31    59.8 1504.41    69.8 1500.96    79.7 1497.96
    99.6 1492.24   129.5 1482.78   139.5  1479.7   149.5 1476.82   159.4 1474.14
   169.4 1471.64   219.2 1460.02   229.2 1457.99   239.2 1456.76   249.1 1456.36
     279 1455.98   318.9 1455.19   356.3 1454.12   368.7 1453.84   371.3 1454.09
   378.7 1454.82   388.6 1457.32   398.6 1460.37   408.6 1463.16   438.4 1471.09
   468.4 1480.06   488.3  1486.2   518.2 1495.91   538.1 1502.81     568 1513.61
#Mann= 3 , 0 , 0
       0      .1       0   356.3    .045       0   371.3      .1       0
Bank Sta=356.3,371.3
XS Rating Curve= 0 ,0
Exp/Cntr=0.3,0.1

Type RM Length L Ch R = 1 ,13493.3 ,242.5,236.1,229.7
XS GIS Cut Line= 3
     1954552.171      412523.026     1954467.402      412820.567
     1954433.001      412984.811
#Sta/Elev= 26
       0 1471.88      10 1470.15    49.9 1463.94    69.9 1460.72    89.8  1457.4
   109.8 1453.93   129.7 1450.26   139.7 1448.51   149.7 1447.29   159.7 1446.87
   265.8 1446.93   280.8 1446.89   289.4 1446.84   299.4 1447.67   309.4 1449.86
   319.2 1452.93   329.1  1455.9     339 1458.61   348.9 1461.42   368.6 1467.48
     418 1483.88   427.8 1487.36   437.7 1491.33   457.4 1500.76   467.3 1504.71
   477.2 1508.34
#Mann= 3 , 0 , 0
       0      .1       0   265.8    .045       0   280.8      .1       0
Bank Sta=265.8,280.8
XS Rating Curve= 0 ,0
Exp/Cntr=0.3,0.1

Type RM Length L Ch R = 1 ,13257.2 ,176,168.8,161.7
XS GIS Cut Line= 3
     1954141.034      412505.151     1954245.308       412628.79
     1954243.818      412986.301
#Sta/Elev= 30
       0 1482.46      19 1480.32    38.1 1477.69    47.6 1476.11    66.6 1472.56
    76.1 1470.61    85.6 1468.34   114.2 1460.72   123.7 1458.44   133.2 1456.45
   161.7 1451.61   191.5 1447.48   211.4 1445.02   221.3 1444.08   241.2 1442.64
   275.1 1440.79   280.9 1440.55   290.1 1440.44   290.8 1440.43   300.8 1440.91
   310.7 1443.04   320.6 1446.33   330.6 1449.31   340.5 1451.89   390.2    1464
     410 1469.43   429.9  1475.4   469.6 1487.93   489.5 1494.64   519.2 1505.49
#Mann= 3 , 0 , 0
       0      .1       0   275.1    .045       0   290.1      .1       0
Bank Sta=275.1,290.1
XS Rating Curve= 0 ,0
Exp/Cntr=0.3,0.1

Type RM Length L Ch R = 1 ,13088.4 ,408.8,401.2,393.6
XS GIS Cut Line= 2
     1953978.167      412426.449     1954224.631       413177.58
#Sta/Elev= 30
       0 1548.06      50 1548.01      60 1547.49      70 1545.01      80  1540.2
    90.1 1534.03   120.1 1513.84   130.1 1507.84   140.1 1502.74   160.1 1494.42
   180.1 1486.79   250.2 1461.65   290.2 1447.98   310.2 1440.09   316.9 1438.11
   320.2 1437.14   330.2 1436.25   331.9 1436.34   350.2 1438.07   400.3 1445.98
   450.3 1455.12   480.3 1461.95   540.4  1480.2   570.4 1492.16   580.4 1495.69
   620.4 1508.66   670.4 1526.41   690.5 1533.07   740.5 1547.68   790.5 1560.81
#Mann= 3 , 0 , 0
       0      .1       0   316.9    .045       0   331.9      .1       0
Bank Sta=316.9,331.9
XS Rating Curve= 0 ,0
Exp/Cntr=0.3,0.1

Type RM Length L Ch R = 1 ,12687.1 ,385.2,389.1,392.9
XS GIS Cut Line= 3
     1953566.781      412730.829     1953766.392      412911.075
     1954058.743       413299.01
#Sta/Elev= 30
       0 1539.44    19.9 1531.83    39.8 1523.78   119.5 1489.78   139.4 1481.75
   159.4 1474.11   169.3 1470.69   199.2 1461.26   229.1 1452.18     269 1439.26
   278.9 1437.06   288.8 1435.95   349.3 1432.33   358.2 1432.11   364.3 1432.82
   368.1 1433.26     378 1436.45   397.8 1444.79   427.6 1456.24   477.1 1476.21
   516.8 1491.78   546.5 1502.84   556.4  1506.3   576.3 1512.71     606 1521.24
   625.8 1526.23   655.6 1533.22   675.4 1537.21     715  1544.2   754.7  1552.6
#Mann= 3 , 0 , 0
       0      .1       0   349.3    .045       0   364.3      .1       0
Bank Sta=349.3,364.3
XS Rating Curve= 0 ,0
Exp/Cntr=0.3,0.1

Type RM Length L Ch R = 1 ,12297.9 ,265.8,269.7,273.6
XS GIS Cut Line= 2
     1953423.777      413037.693     1953706.784      413587.379
#Sta/Elev= 30
       0 1488.26    19.9 1476.46    39.9 1465.82    79.8 1446.45    89.8 1442.56
    99.7  1440.3   179.5 1432.64   211.2 1429.36   219.4 1428.77   226.2 1429.31
   229.4 1429.56   239.3 1432.43   249.3 1436.06   259.3 1439.26   269.2 1441.94
   299.2 1449.32   329.1 1457.84     349 1464.43   378.9 1474.94   408.8 1484.56
   448.7 1495.34   488.6 1507.45   518.5 1515.44   528.5 1518.38   558.4 1527.83
   568.4 1530.36   578.4 1532.53   588.4 1534.36   608.3 1537.24   618.3 1538.26
#Mann= 3 , 0 , 0
       0      .1       0   211.2    .045       0   226.2      .1       0
Bank Sta=211.2,226.2
XS Rating Curve= 0 ,0
Exp/Cntr=0.3,0.1

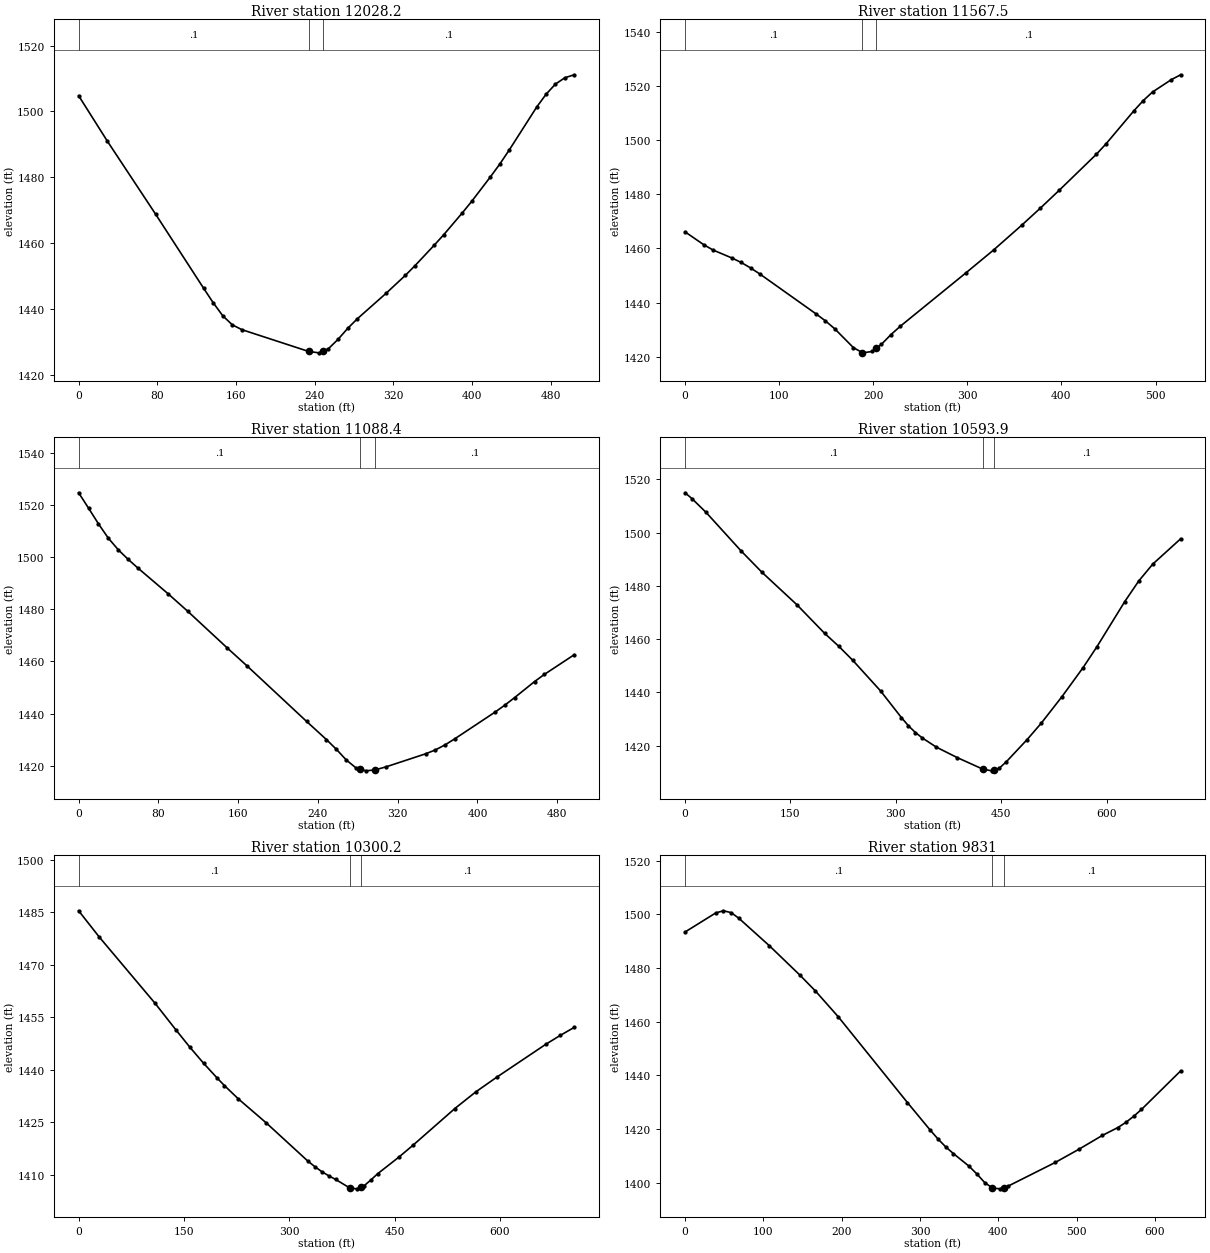
Type RM Length L Ch R = 1 ,12028.2 ,435.9,460.6,485.3
XS GIS Cut Line= 3
     1953204.802      413107.706     1953315.034      413462.237
     1953362.702      413585.877
#Sta/Elev= 30
       0  1504.8    29.3 1490.94    78.2 1468.82     127 1446.31   136.8 1441.88
   146.6 1437.89   156.3 1435.15   166.1 1433.68   233.9 1427.07   244.3 1426.65
   248.9 1427.25     254 1427.92   263.8 1430.77   273.6  1434.1   283.3 1436.99
   312.6 1444.75   332.2 1450.21     342 1453.15   361.5 1459.36   371.3 1462.59
   390.2 1469.23   399.7 1472.72   418.6 1480.11   428.1 1483.99   437.5 1488.17
   465.9 1501.44   475.4  1505.3   484.8 1508.34   494.3 1510.25   503.8 1511.16
#Mann= 3 , 0 , 0
       0      .1       0   233.9    .045       0   248.9      .1       0
Bank Sta=233.9,248.9
XS Rating Curve= 0 ,0
Exp/Cntr=0.3,0.1

Type RM Length L Ch R = 1 ,11567.5 ,462.5,478.9,495.2
XS GIS Cut Line= 2
     1952987.316      413167.291     1952613.419      413538.209
#Sta/Elev= 30
       0 1466.08    19.9 1461.33    29.8 1459.37    49.7 1456.45    59.6 1454.79
    69.6 1452.77    79.5 1450.52   139.1 1435.82   149.1 1433.24     159 1430.31
   178.9 1423.34   188.2 1421.54   188.8 1421.42   198.7 1421.92   203.2 1423.11
   208.7 1424.57   218.6 1428.08   228.6  1431.2   298.1 1450.84   327.9  1459.4
   357.7 1468.52   377.6 1474.85   397.5 1481.39   437.2 1494.76   447.2 1498.51
     477 1510.79   486.9 1514.54   496.9 1517.75   516.7 1522.27   526.7 1524.09
#Mann= 3 , 0 , 0
       0      .1       0   188.2    .045       0   203.2      .1       0
Bank Sta=188.2,203.2
XS Rating Curve= 0 ,0
Exp/Cntr=0.3,0.1

Type RM Length L Ch R = 1 ,11088.4 ,510.4,494.4,478.4
XS GIS Cut Line= 2
     1953104.996      412851.489      1952608.95      412882.772
#Sta/Elev= 30
       0 1524.78     9.9 1518.91    19.9 1512.85    29.8 1507.34    39.8 1502.88
    49.7 1499.21    59.6 1495.83    89.5 1486.08   109.4 1479.29   149.1 1465.18
     169 1458.27   228.6    1437   248.5 1430.03   258.5 1426.28   268.4  1422.2
   278.3  1419.1   282.6 1418.63   288.3 1418.01   297.6  1418.4   308.2 1419.53
   347.9 1424.53   357.9 1426.06   367.8 1428.04   377.7 1430.42   417.5 1440.52
   427.4 1443.22   437.4 1446.17   457.3  1452.3   467.2 1455.06     497 1462.58
#Mann= 3 , 0 , 0
       0      .1       0   282.6    .045       0   297.6      .1       0
Bank Sta=282.6,297.6
XS Rating Curve= 0 ,0
Exp/Cntr=0.3,0.1

Type RM Length L Ch R = 1 ,10593.9 ,296.9,293.6,290.3
XS GIS Cut Line= 3
      1952890.49      412346.505     1952554.578      412469.399
      1952305.81      412712.209
#Sta/Elev= 30
       0 1514.91     9.9 1512.69    29.8 1507.56    79.5 1493.15   109.3  1485.1
     159 1472.93   198.7 1462.14   218.6 1457.34   238.5 1452.08   278.2 1440.56
     308 1430.52   317.9 1427.47   327.9 1424.93   337.8 1422.88   357.7 1419.45
   387.5 1415.52   424.4 1411.13   437.1 1410.57   439.4 1410.79   447.1 1411.54
     457 1413.92   486.8  1422.3   506.7 1428.38   536.5 1438.45   566.3 1449.25
   586.1 1457.12   625.8  1474.1   645.7 1481.82   665.6 1488.14   705.3 1497.64
#Mann= 3 , 0 , 0
       0      .1       0   424.4    .045       0   439.4      .1       0
Bank Sta=424.4,439.4
XS Rating Curve= 0 ,0
Exp/Cntr=0.3,0.1

Type RM Length L Ch R = 1 ,10300.2 ,498.5,469.3,440
XS GIS Cut Line= 3
     1952665.507      412083.363     1952354.037      412255.638
     1952136.737      412529.729
#Sta/Elev= 30
       0 1485.42    29.7 1477.85   108.8 1459.02   138.4 1451.46   158.2 1446.52
     178 1441.88   197.7 1437.58   207.6 1435.53   227.4 1431.73     267  1424.9
   326.3 1413.99   336.2  1412.4     346 1410.99   355.9  1409.8   365.9 1408.73
   385.9 1406.32   386.8 1406.29   395.9 1406.04   401.8 1406.49   405.9 1406.81
   415.9 1408.52   425.9 1410.36   455.9 1415.07   475.9 1418.44   535.8 1428.97
   565.8 1433.75   595.8 1437.96   665.7 1447.36   685.7 1449.82   705.7 1452.12
#Mann= 3 , 0 , 0
       0      .1       0   386.8    .045       0   401.8      .1       0
Bank Sta=386.8,401.8
XS Rating Curve= 0 ,0
Exp/Cntr=0.3,0.1

Type RM Length L Ch R = 1 ,9831    ,283.5,296.2,309
XS GIS Cut Line= 3
      1951728.12      411997.544     1951952.954      412269.044
      1952119.42      412494.723
#Sta/Elev= 30
       0 1493.46    39.2 1500.57      49 1501.36    58.8 1500.67    68.5 1498.61
   107.7 1488.32   146.9 1477.31   166.5 1471.46   195.8 1461.81     284 1429.89
   313.3 1419.56   323.1 1416.31   332.9 1413.38   342.7 1410.89   362.5 1406.23
   372.5 1403.34   382.6 1400.11   391.8 1398.21   392.6 1398.05   402.6 1397.76
   406.8 1398.19   412.6 1398.78   472.7 1407.58   502.7 1412.46   532.8 1417.64
   552.8 1420.61   562.8 1422.49   572.8 1424.75   582.9 1427.34   632.9  1441.7
#Mann= 3 , 0 , 0
       0      .1       0   391.8    .045       0   406.8      .1       0
Bank Sta=391.8,406.8
XS Rating Curve= 0 ,0
Exp/Cntr=0.3,0.1

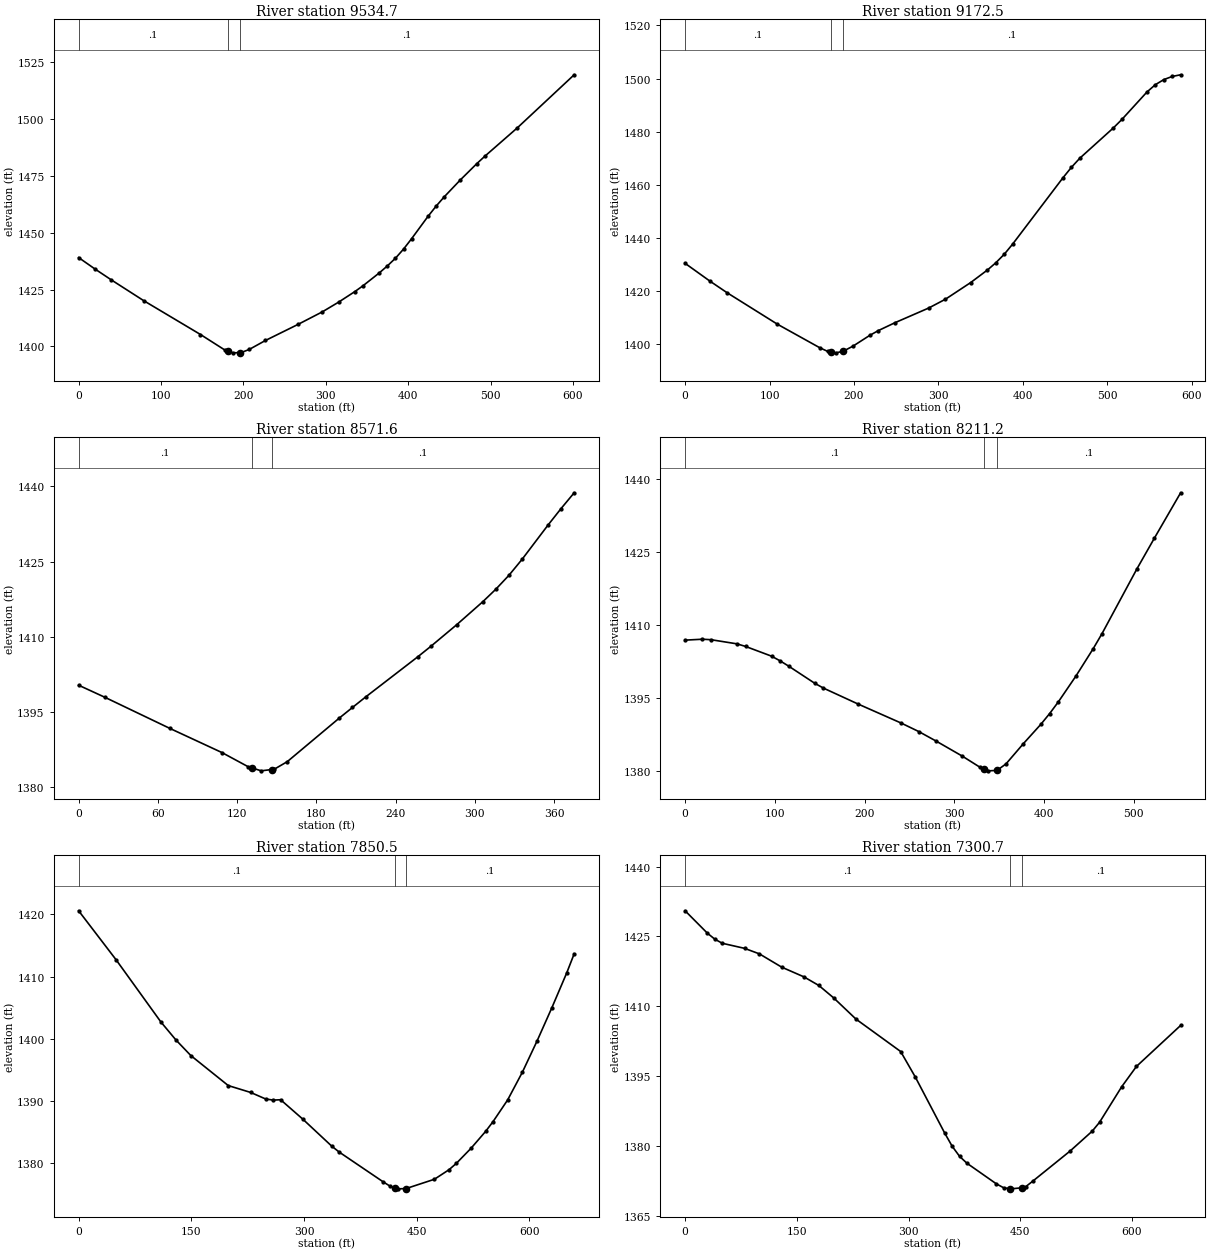
Type RM Length L Ch R = 1 ,9534.7  ,361,362.2,363.5
XS GIS Cut Line= 2
     1951711.634      412255.638     1951754.562      412855.458
#Sta/Elev= 30
       0 1439.09    19.7  1434.1    39.4 1429.34    78.9 1420.16   147.9 1405.26
   177.4 1398.45   180.8 1398.02   187.3  1397.2   195.8  1397.3   197.2 1397.32
     207 1398.68   226.7 1402.63   266.2 1409.69   295.8 1415.23   315.5 1419.49
   335.2 1424.13     345 1426.66   364.8 1432.32   374.6  1435.4   384.5  1438.8
   394.3 1442.81   404.2 1447.43   423.9 1457.16   433.8 1461.68   443.6 1465.76
   463.3 1473.25     483 1480.31   492.9 1483.63   532.4 1496.13   601.4 1519.47
#Mann= 3 , 0 , 0
       0      .1       0   180.8    .045       0   195.8      .1       0
Bank Sta=180.8,195.8
XS Rating Curve= 0 ,0
Exp/Cntr=0.3,0.1

Type RM Length L Ch R = 1 ,9172.5  ,598.6,600.6,602.6
XS GIS Cut Line= 2
     1951361.944      412298.092     1951370.849      412884.912
#Sta/Elev= 30
       0 1430.46    29.8 1423.68    49.7 1419.41   109.4 1407.54   159.2 1398.75
   169.1 1397.29   172.5 1397.11     179 1396.78   187.5 1397.43   198.9 1399.31
   218.8 1403.37   228.8 1405.14   248.7 1408.14   288.5 1413.64   308.4 1416.97
   338.2 1423.22   358.1 1427.96     368 1430.67     378 1433.88   387.9 1437.69
   447.6 1462.69   457.6 1466.61   467.5 1470.03   507.3 1481.44   517.3  1484.6
   547.1 1494.97     557  1497.7     567 1499.61   576.9 1500.79   586.9 1501.42
#Mann= 3 , 0 , 0
       0      .1       0   172.5    .045       0   187.5      .1       0
Bank Sta=172.5,187.5
XS Rating Curve= 0 ,0
Exp/Cntr=0.3,0.1

Type RM Length L Ch R = 1 ,8571.6  ,322.4,360.1,397.8
XS GIS Cut Line= 2
     1950799.981      412362.891     1950772.051       412737.16
#Sta/Elev= 23
       0 1400.32    19.8 1397.92    69.1  1391.7   108.6 1386.87   128.4 1384.05
   131.1 1383.83   138.3 1383.23   146.1 1383.49   148.2 1383.56     158 1385.06
   197.5 1393.78   207.4 1395.88   217.3 1397.96   256.8 1405.98   266.7 1408.07
   286.4 1412.41   306.2 1417.01     316 1419.49   325.9 1422.26   335.8 1425.43
   355.6 1432.32   365.4 1435.59   375.3 1438.73
#Mann= 3 , 0 , 0
       0      .1       0   131.1    .045       0   146.1      .1       0
Bank Sta=131.1,146.1
XS Rating Curve= 0 ,0
Exp/Cntr=0.3,0.1

Type RM Length L Ch R = 1 ,8211.2  ,352.7,360.9,369.3
XS GIS Cut Line= 3
     1950840.201      412298.092     1950606.702      412357.305
      1950299.28       412307.03
#Sta/Elev= 30
       0 1406.85    19.3 1407.04    28.9 1406.94    57.8 1406.09    67.4 1405.56
    96.4 1403.56     106 1402.59   115.6  1401.5   144.5    1398   154.2 1397.01
   192.7 1393.75   240.9 1389.83   260.4  1388.1   279.8 1386.14     309 1383.05
   328.5 1380.79   332.7 1380.46   338.2 1380.03   347.7 1380.12   357.7 1381.45
   377.2 1385.63   396.6 1389.58   406.4 1391.79   416.1 1394.19   435.6 1399.46
     455 1405.12   464.8  1408.2   503.7 1421.49   523.2  1427.8   552.4 1437.09
#Mann= 3 , 0 , 0
       0      .1       0   332.7    .045       0   347.7      .1       0
Bank Sta=332.7,347.7
XS Rating Curve= 0 ,0
Exp/Cntr=0.3,0.1

Type RM Length L Ch R = 1 ,7850.5  ,588.3,549.6,510.8
XS GIS Cut Line= 4
      1951058.06      412010.966     1950810.036      412114.868
     1950550.841      411959.574     1950469.284      411994.208
#Sta/Elev= 30
       0 1420.59    49.8 1412.71   109.6 1402.67   129.5 1399.79   149.4 1397.27
   199.2 1392.44   229.1 1391.33     249 1390.28     259  1390.1   268.9 1390.16
   298.2 1387.06   337.1 1382.67   346.9 1381.73   405.4 1376.94   415.1  1376.2
   420.8 1375.97   424.9 1375.81   435.8 1375.85   473.6 1377.35   493.1 1378.89
   502.8 1379.91   522.3 1382.33   541.8 1385.06   551.6 1386.62   571.1 1390.12
   590.8 1394.61   610.4 1399.65   630.1    1405   649.8 1410.59   659.7 1413.66
#Mann= 3 , 0 , 0
       0      .1       0   420.8    .045       0   435.8      .1       0
Bank Sta=420.8,435.8
XS Rating Curve= 0 ,0
Exp/Cntr=0.3,0.1

Type RM Length L Ch R = 1 ,7300.7  ,252.7,244.1,235.4
XS GIS Cut Line= 3
     1950899.414      411457.941     1950637.984      411581.953
     1950491.628      411928.292
#Sta/Elev= 30
       0  1430.5    29.9 1425.69    39.9  1424.4    49.9 1423.52    79.8 1422.43
    99.8 1421.24   129.7 1418.39   159.6  1416.3   179.6 1414.45   199.6 1411.77
   229.5 1407.22   289.4 1400.27   309.1 1394.78   348.7  1382.7   358.6 1379.91
   368.5 1377.75   378.4 1376.27     418 1371.83   427.9 1370.98   436.8 1370.79
   437.8 1370.77   451.8 1370.99   457.6 1371.27   467.4  1372.5   516.9 1378.89
   546.6 1383.16   556.5 1385.08   586.2 1392.71     606 1397.07   665.3 1405.87
#Mann= 3 , 0 , 0
       0      .1       0   436.8    .045       0   451.8      .1       0
Bank Sta=436.8,451.8
XS Rating Curve= 0 ,0
Exp/Cntr=0.3,0.1

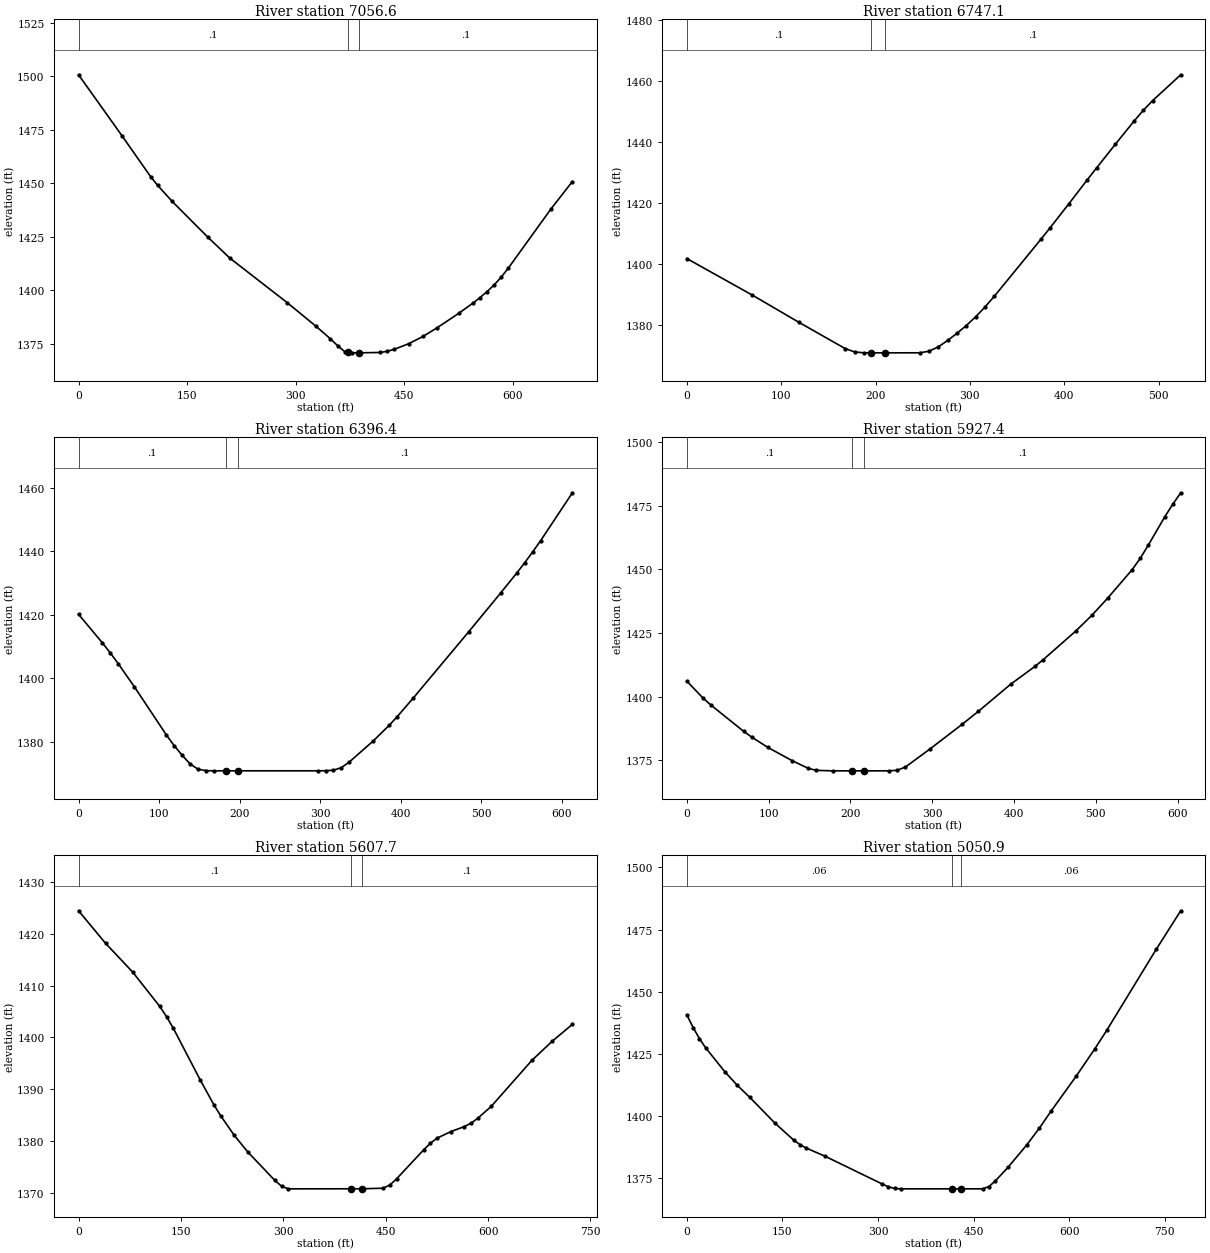
Type RM Length L Ch R = 1 ,7056.6  ,310.2,309.5,308.8
XS GIS Cut Line= 3
     1950365.343      411272.358      1950362.03      411600.946
     1950355.327      411955.105
#Sta/Elev= 30
       0 1500.72    59.8 1472.34    99.6 1453.14   109.5 1448.98   129.4 1441.56
   179.2 1424.68   209.1 1415.06   288.8 1394.14   328.6  1383.1   348.3 1377.31
   358.1 1374.13     368 1371.34   372.1 1371.13   377.8 1370.83   387.1 1370.77
   417.2 1370.94     427  1371.5   436.8 1372.46   456.5 1375.04   476.2 1378.42
   495.9 1382.51   525.4 1389.18   545.1 1393.95   554.9 1396.55   564.8 1399.38
   574.6  1402.5   584.4 1406.16   594.3 1410.42   653.3 1438.07   682.8 1450.84
#Mann= 3 , 0 , 0
       0      .1       0   372.1    .045       0   387.1      .1       0
Bank Sta=372.1,387.1
XS Rating Curve= 0 ,0
Exp/Cntr=0.3,0.1

Type RM Length L Ch R = 1 ,6747.1  ,347.3,350.9,354.6
XS GIS Cut Line= 3
     1950063.732      411513.802     1950068.104      411809.868
     1950103.952      412034.428
#Sta/Elev= 27
       0 1401.72    69.1 1389.78   118.4 1380.86   167.8 1372.17   177.7 1371.09
   187.5 1370.77   195.4 1370.77   210.4 1370.77   246.8 1370.78   256.6  1371.3
   266.5 1372.73   276.4 1374.83   286.2 1377.16   296.1  1379.7     306 1382.57
   315.9 1385.78   325.8 1389.31   375.2 1408.02   385.1 1411.85   404.9 1419.71
   424.6 1427.66   434.5 1431.57   454.3  1439.3   474.1  1446.9     484 1450.46
   493.8 1453.62   523.5 1462.08
#Mann= 3 , 0 , 0
       0      .1       0   195.4    .045       0   210.4      .1       0
Bank Sta=195.4,210.4
XS Rating Curve= 0 ,0
Exp/Cntr=0.3,0.1

Type RM Length L Ch R = 1 ,6396.4  ,442.3,468.4,494.5
XS GIS Cut Line= 2
     1949751.096      411498.161     1949703.987      412109.282
#Sta/Elev= 30
       0 1420.11    29.7 1411.08    39.5  1407.9    49.4  1404.5    69.2 1397.29
   108.8 1382.15   118.6 1378.74   128.5 1375.69   138.4 1372.94   148.3 1371.27
   158.2 1370.82   168.1 1370.76   182.5 1370.77   197.5 1370.77   296.6 1370.77
   306.5 1370.79   316.4 1370.97   326.2 1371.77   336.1 1373.56   365.8  1380.2
   385.6 1385.14   395.4 1387.82   415.2 1393.65   484.4 1414.66     524 1426.87
   543.7 1433.08   553.6 1436.33   563.5 1439.73   573.4  1443.3   612.9 1458.42
#Mann= 3 , 0 , 0
       0      .1       0   182.5    .045       0   197.5      .1       0
Bank Sta=182.5,197.5
XS Rating Curve= 0 ,0
Exp/Cntr=0.3,0.1

Type RM Length L Ch R = 1 ,5927.4  ,319.1,319.7,320.4
XS GIS Cut Line= 2
     1949603.623      411475.817     1949024.157      411645.634
#Sta/Elev= 30
       0 1406.03    19.8 1399.38    29.7 1396.57    69.3 1386.34    79.2 1384.06
      99 1379.98   128.7 1374.78   148.5 1371.73   158.4 1370.96   178.2 1370.77
   201.7 1370.77   216.7 1370.77   247.5 1370.77   257.4 1371.01   267.3 1372.29
     297 1379.31   336.6 1389.08   356.4 1394.18     396 1404.87   425.7 1411.89
   435.6 1414.48   475.2 1425.69     495  1431.9   514.8 1438.82   544.4  1449.9
   554.3 1454.37   564.2 1459.58     584 1470.55   593.9 1475.57   603.8 1480.16
#Mann= 3 , 0 , 0
       0      .1       0   201.7    .045       0   216.7      .1       0
Bank Sta=201.7,216.7
XS Rating Curve= 0 ,0
Exp/Cntr=0.3,0.1

Type RM Length L Ch R = 1 ,5607.7  ,564.1,556.7,549.3
XS GIS Cut Line= 3
     1949701.938      411118.306     1949523.183      411177.891
     1949004.792      411310.468
#Sta/Elev= 30
       0 1424.48    39.7 1418.18    79.3 1412.64     119    1406   128.9 1404.03
   138.8 1401.79   178.5 1391.74   198.3 1386.99   208.2 1384.88   228.1  1381.1
   247.9 1377.89   287.5  1372.4   297.4 1371.27   307.3 1370.76   399.7 1370.77
   414.7 1370.77     446 1370.88     456 1371.49   465.9 1372.69   505.5 1378.28
   515.4 1379.56   525.3 1380.56   545.1  1381.8     565 1382.78   574.9 1383.44
   584.8 1384.38   604.6 1386.69     664 1395.56   693.8 1399.26   723.5 1402.54
#Mann= 3 , 0 , 0
       0      .1       0   399.7    .045       0   414.7      .1       0
Bank Sta=399.7,414.7
XS Rating Curve= 0 ,0
Exp/Cntr=0.3,0.1

Type RM Length L Ch R = 1 ,5050.9  ,315.1,321.3,327.5
XS GIS Cut Line= 3
     1949388.087      410545.581      1948933.29      410842.724
     1948741.127      410972.322
#Sta/Elev= 30
       0 1440.68     9.9  1435.6    19.8 1431.16    29.6 1427.45    59.3 1417.94
      79 1412.42    98.8 1407.55   138.3 1397.17   167.9 1390.31   177.8 1388.52
   187.7 1387.12   217.3 1383.83   306.2 1372.76   316.1 1371.62     326 1370.93
   335.8 1370.77   415.8 1370.77   430.8 1370.77   464.2 1370.78   474.1 1371.71
     484 1373.93   503.8 1379.37   533.4 1388.44   552.9 1395.08   572.2 1402.26
   610.9 1416.06   639.8 1426.91   659.2 1434.64   736.4 1467.03     775 1482.59
#Mann= 3 , 0 , 0
       0     .06       0   415.8    .045       0   430.8     .06       0
Bank Sta=415.8,430.8
XS Rating Curve= 0 ,0
Exp/Cntr=0.3,0.1