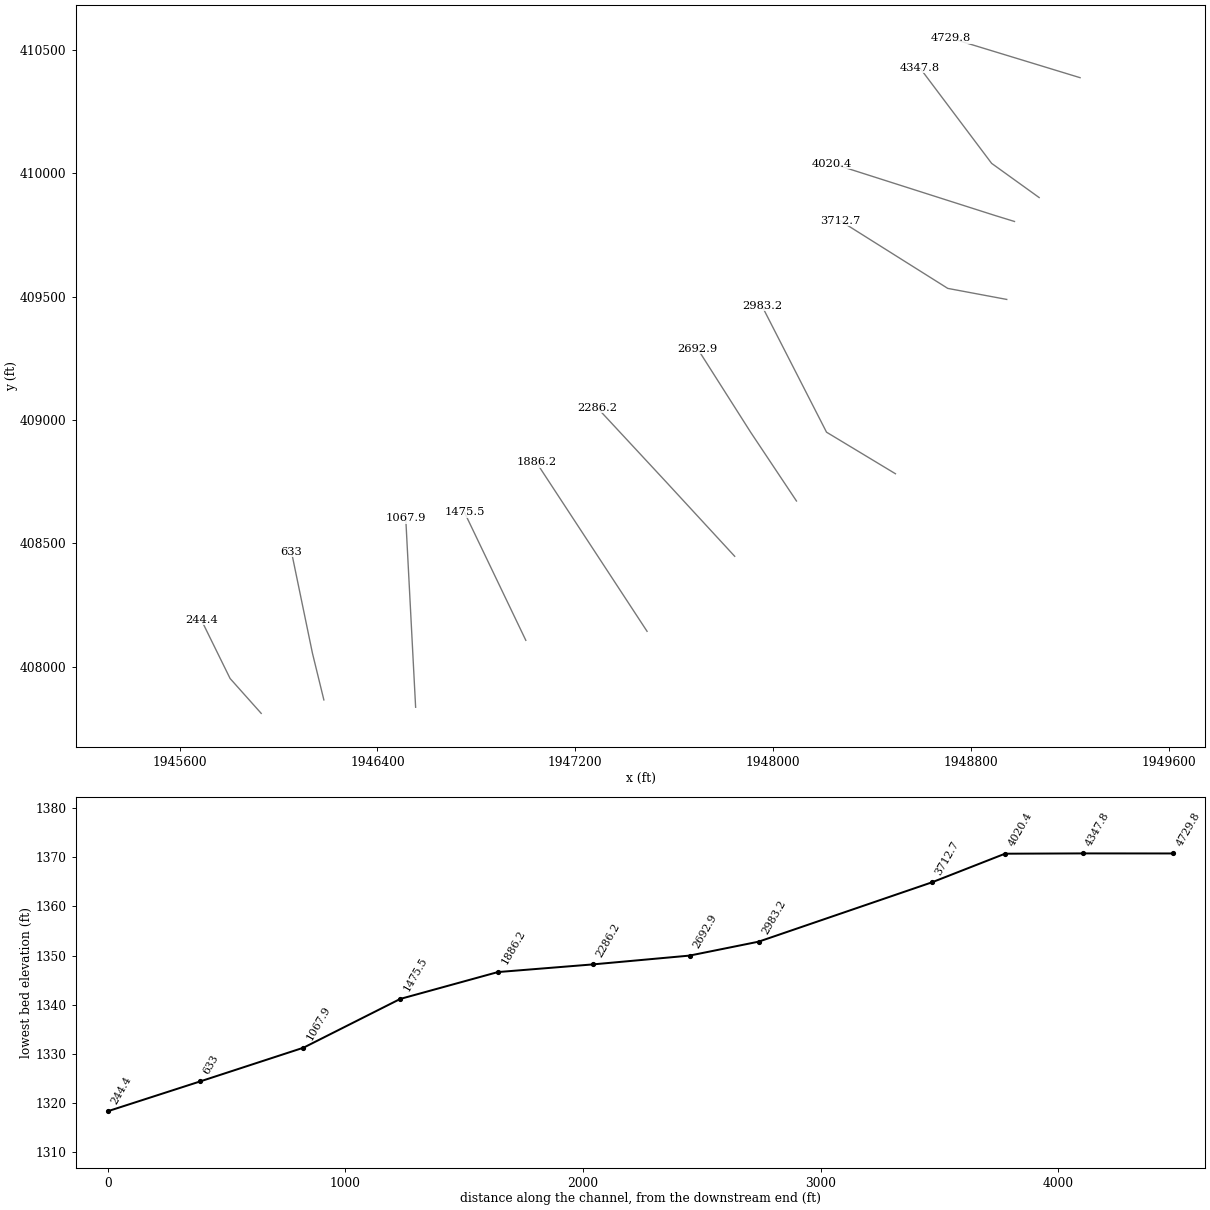
HEC-RAS study OsbrneCrk.prj: OsbrneCrk

--- OsbrneCrk.g01 (geometry) --- (continued)

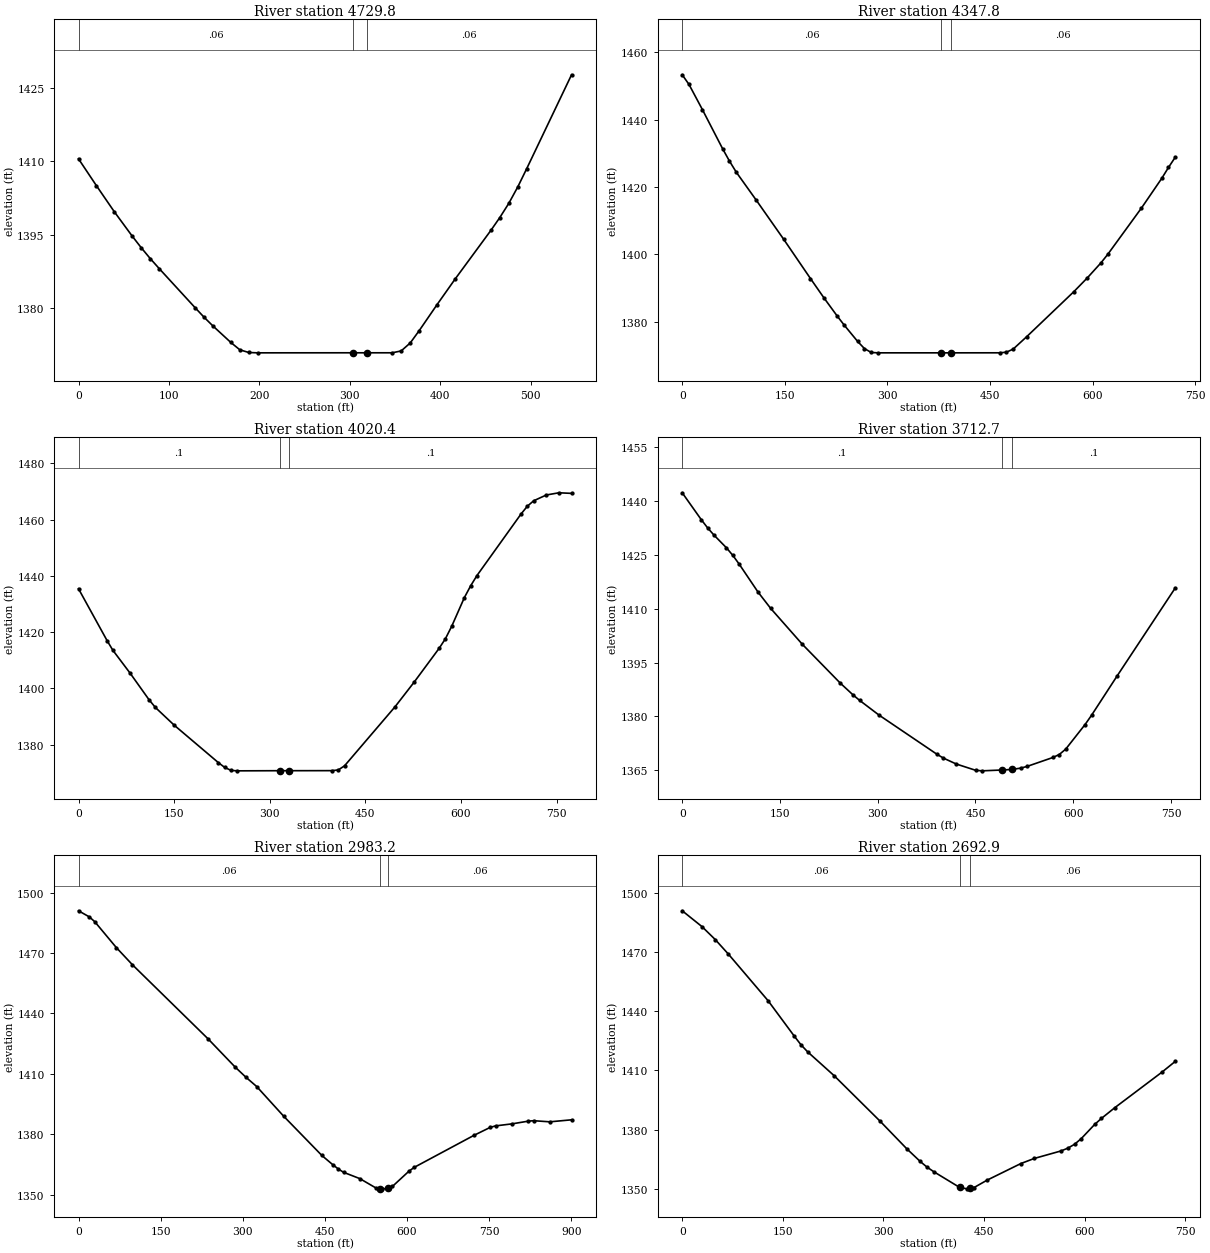
Type RM Length L Ch R = 1 ,4729.8  ,395.9,381.8,367.7
XS GIS Cut Line= 2
     1949240.153      410386.898     1948718.783      410546.288
#Sta/Elev= 28
       0 1410.53    19.8 1405.03    39.6 1399.68    59.5 1394.66    69.4  1392.3
    79.3 1390.09    89.2 1388.04   128.9 1380.02   138.8 1378.07   148.7 1376.26
   168.5 1372.88   178.4 1371.38   188.3 1370.83   198.2 1370.76   303.6 1370.77
   318.6 1370.77   346.9 1370.77   356.8 1371.15   366.8 1372.78   376.7  1375.3
   396.5 1380.65   416.3 1385.85     456 1395.86   465.9  1398.5   475.8  1401.4
   485.7 1404.76   495.6 1408.51   545.2 1427.76
#Mann= 3 , 0 , 0
       0     .06       0   303.6    .045       0   318.6     .06       0
Bank Sta=303.6,318.6
XS Rating Curve= 0 ,0
Exp/Cntr=0.3,0.1

Type RM Length L Ch R = 1 ,4347.8  ,312.8,326.9,340.9
XS GIS Cut Line= 3
     1949074.804      409901.279     1948882.642      410039.814
     1948592.164      410427.118
#Sta/Elev= 30
       0 1453.36     9.9 1450.49    29.6 1442.98    59.2 1431.34    69.1 1427.72
      79 1424.44   108.6 1416.02   148.1 1404.58   187.5 1392.85   207.3 1387.08
     227  1381.6   236.9    1379   256.6 1374.14   266.5 1372.03   276.4 1370.88
   286.3 1370.77   378.4 1370.77   393.4 1370.77   464.1 1370.78     474 1370.96
   483.9 1371.87   503.7 1375.56   572.8 1388.96   592.6 1393.08   612.3 1397.49
   622.2    1400   671.6 1413.79   701.3 1422.61   711.1 1425.84     721 1428.88
#Mann= 3 , 0 , 0
       0     .06       0   378.4    .045       0   393.4     .06       0
Bank Sta=378.4,393.4
XS Rating Curve= 0 ,0
Exp/Cntr=0.3,0.1

Type RM Length L Ch R = 1 ,4020.4  ,313.8,307.5,301.2
XS GIS Cut Line= 3
     1948974.999      409804.453     1948897.538      409828.287
     1948238.013      410039.173
#Sta/Elev= 30
       0 1435.41      45 1416.91      54 1413.52      81  1405.4   110.7 1395.96
   120.6 1393.23   150.3  1386.9   219.5 1373.61   229.4 1371.92   239.3 1370.87
   249.2 1370.71   315.9 1370.76   330.9 1370.76   397.6 1370.78   407.5 1371.02
   417.4  1372.5   496.5 1393.45   526.2 1402.12   565.7 1414.22   575.6 1417.64
   585.5 1422.08   605.3 1432.24   615.2 1436.45   625.1  1440.1   694.3 1461.98
   704.2 1464.75   714.1 1466.67   733.9 1468.72   753.7 1469.51   773.5  1469.3
#Mann= 3 , 0 , 0
       0      .1       0   315.9    .045       0   330.9      .1       0
Bank Sta=315.9,330.9
XS Rating Curve= 0 ,0
Exp/Cntr=0.3,0.1

Type RM Length L Ch R = 1 ,3712.7  ,741,729.4,717.8
XS GIS Cut Line= 3
     1948943.717      409488.651     1948705.376       409533.34
     1948270.405      409807.432
#Sta/Elev= 30
       0 1442.18    29.1 1434.74    38.8 1432.46    48.5 1430.46    67.9 1426.88
    77.6 1424.79    87.3 1422.38   116.4 1414.56   135.8 1410.03   184.3 1400.07
   242.5 1389.28   262.3 1385.97   272.2 1384.48   301.8 1380.41   390.8 1369.51
   400.7 1368.44   420.5 1366.79   450.1 1365.05     460 1364.89   490.8 1365.12
   505.8 1365.28   519.3 1365.64   529.2 1366.12   568.8  1368.6   578.6 1369.43
   588.5 1370.93   618.2 1377.76   628.1 1380.33   667.6 1391.33   756.6 1415.73
#Mann= 3 , 0 , 0
       0      .1       0   490.8    .045       0   505.8      .1       0
Bank Sta=490.8,505.8
XS Rating Curve= 0 ,0
Exp/Cntr=0.3,0.1

Type RM Length L Ch R = 1 ,2983.2  ,288.6,290.3,290.9
XS GIS Cut Line= 3
     1948493.849      408782.567     1948215.288      408950.895
     1947953.808      409463.149
#Sta/Elev= 30
       0 1491.07    19.7 1488.04    29.6 1485.67      69  1472.8    98.6  1464.2
   236.7 1427.38     286  1413.4   305.7 1408.33   325.5 1403.68     375 1388.86
   444.5 1369.42   464.3 1364.86   474.2 1362.77   484.1 1361.04   513.9  1357.9
   543.6  1353.2   549.8 1352.96   553.5 1352.82   564.8 1353.01   573.4 1354.02
   603.1 1361.47     613 1363.47   722.1 1379.38   751.9 1383.36   761.8 1384.12
   791.5 1385.11   821.3 1386.46   831.2  1386.7   860.9 1386.14   900.6 1387.14
#Mann= 3 , 0 , 0
       0     .06       0   549.8    .045       0   564.8     .06       0
Bank Sta=549.8,564.8
XS Rating Curve= 0 ,0
Exp/Cntr=0.3,0.1

Type RM Length L Ch R = 1 ,2692.9  ,402.2,406.7,412.4
XS GIS Cut Line= 3
     1948093.785      408672.175     1947908.425      408950.895
     1947693.918      409289.041
#Sta/Elev= 30
       0 1490.82    29.5 1482.79    49.2 1476.26    68.9 1468.85     128 1445.29
   167.4 1427.19   177.2  1422.9     187 1419.38   226.4 1407.34   295.4 1384.14
   334.7 1370.33   354.8 1363.88   364.8 1361.06   374.8 1358.73   413.8 1350.68
   424.8 1349.99   428.8 1350.23   434.8 1350.58   454.9 1354.44   504.9 1362.79
   524.9 1365.38     565  1369.2     575  1370.6     585 1372.55     595 1375.42
     615  1382.6     625 1385.63   645.1 1391.11   715.2 1409.05   735.2 1414.54
#Mann= 3 , 0 , 0
       0     .06       0   413.8    .045       0   428.8     .06       0
Bank Sta=413.8,428.8
XS Rating Curve= 0 ,0
Exp/Cntr=0.3,0.1

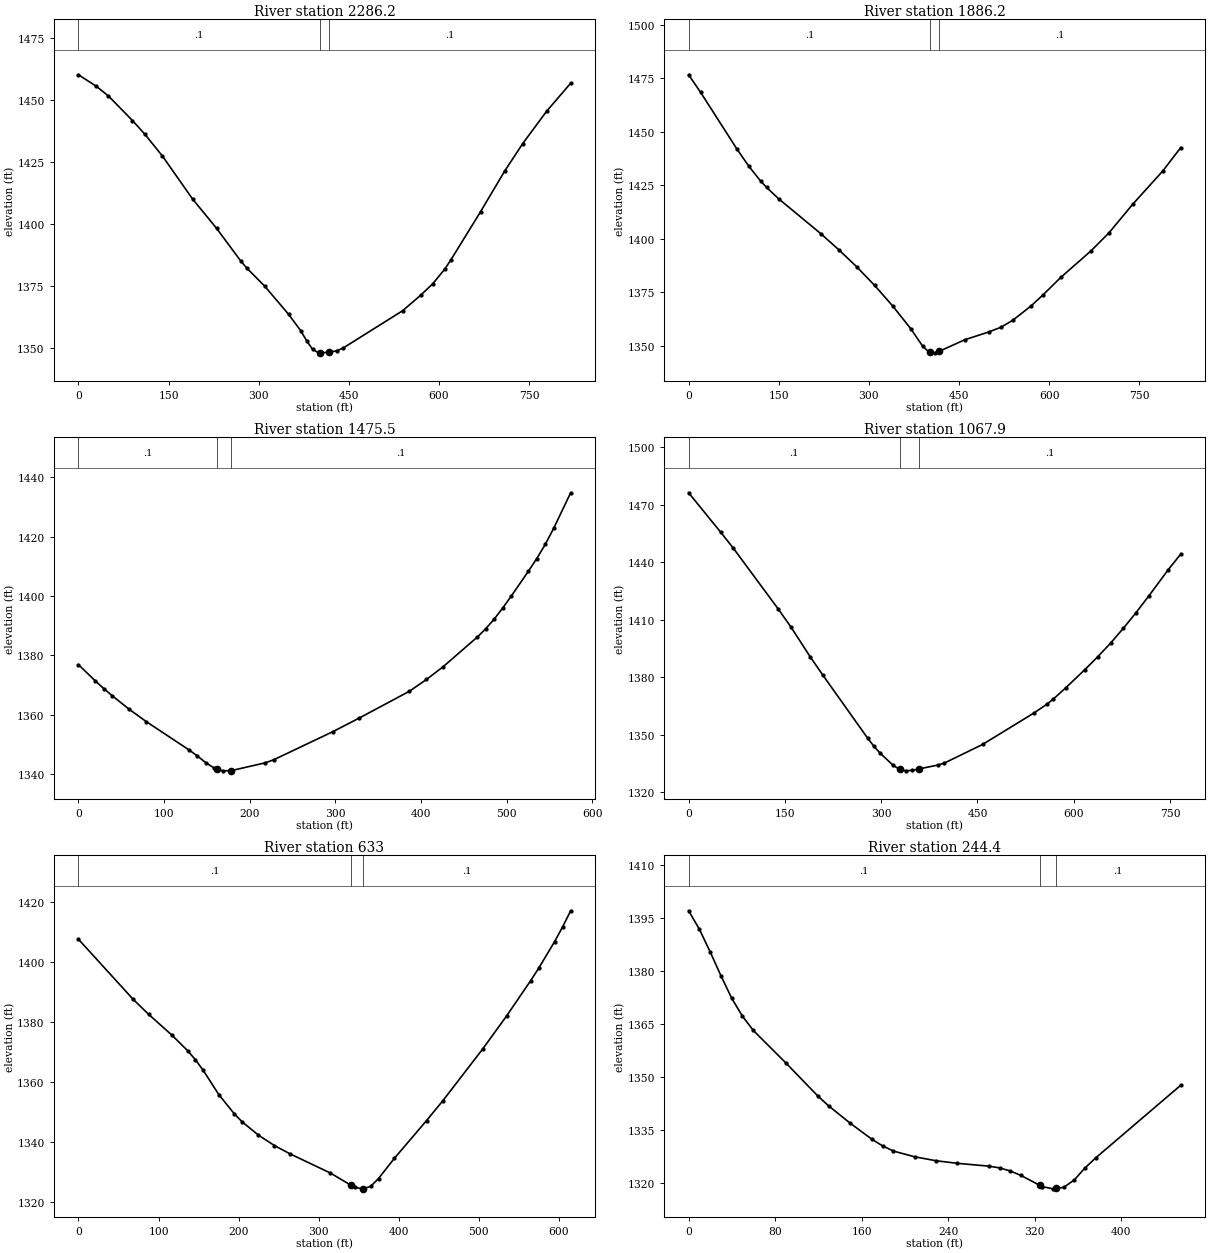
Type RM Length L Ch R = 1 ,2286.2  ,403.7,400,396.2
XS GIS Cut Line= 3
     1947844.098      408448.133     1947566.844      408749.497
     1947288.531      409049.888
#Sta/Elev= 30
       0 1460.04      30 1455.37    49.9  1451.5    89.9 1441.63   109.9 1436.29
   139.8 1427.33   189.8 1410.09   229.7 1398.31   269.7 1385.26   279.7 1382.39
   309.6 1375.09   349.6 1363.72   369.6 1357.17   379.5 1353.15   389.5 1349.62
   399.5  1348.2     402  1348.2     417 1348.43   429.5 1349.01   439.5    1350
   539.3 1365.12   569.3 1371.34   589.3 1375.93   609.3  1381.8   619.2  1385.4
   669.2 1405.01   709.1 1421.27   739.1 1432.33     779 1445.37     819 1456.64
#Mann= 3 , 0 , 0
       0      .1       0     402    .045       0     417      .1       0
Bank Sta=402,417
XS Rating Curve= 0 ,0
Exp/Cntr=0.3,0.1

Type RM Length L Ch R = 1 ,1886.2  ,413.7,410.7,407.7
XS GIS Cut Line= 3
      1947489.81      408144.283     1947265.711      408487.022
     1947041.613      408829.761
#Sta/Elev= 30
       0 1476.74      20 1468.51    79.9 1442.19    99.9 1434.07   119.8 1427.01
   129.8 1424.02   149.8 1418.72   219.7 1402.46   249.7 1394.92   279.7  1386.9
   309.6 1378.16   339.6 1368.56   369.6 1357.95   389.5 1349.73   399.5  1347.1
     402 1346.98   409.5 1346.64     417 1347.35   459.4 1352.75   499.4  1356.4
   519.4 1358.57   539.3 1361.85   569.3 1368.46   589.3 1373.64   619.2 1381.91
   669.2 1394.27   699.2 1402.69   739.1  1416.2     789 1431.73     819 1442.71
#Mann= 3 , 0 , 0
       0      .1       0     402    .045       0     417      .1       0
Bank Sta=402,417
XS Rating Curve= 0 ,0
Exp/Cntr=0.3,0.1

Type RM Length L Ch R = 1 ,1475.5  ,416.4,407.3,398.2
XS GIS Cut Line= 2
     1946999.751      408107.765     1946751.692      408626.209
#Sta/Elev= 30
       0 1376.91    19.8  1371.4    29.7 1368.85    39.6 1366.41    59.5 1361.84
    79.3 1357.72   128.8 1348.28   138.7 1346.21   148.6 1343.95   158.6 1342.08
   161.9 1341.78   168.5 1341.18   178.4 1341.25     218 1343.87   227.9 1344.89
   297.3  1354.4     327 1358.82   386.5 1367.97   406.3 1371.92   426.1 1376.28
   465.7 1386.19   475.6 1389.01   485.6  1392.3   495.5 1396.02   505.4    1400
   525.2 1408.29   535.1 1412.59     545 1417.35   554.9  1422.8   574.7 1434.75
#Mann= 3 , 0 , 0
       0      .1       0   161.9    .045       0   178.4      .1       0
Bank Sta=161.9,178.4
XS Rating Curve= 0 ,0
Exp/Cntr=0.3,0.1

Type RM Length L Ch R = 1 ,1067.9  ,431.5,434.9,438.3
XS GIS Cut Line= 2
     1946554.352      407836.652     1946514.379      408602.348
#Sta/Elev= 30
       0 1476.14    49.8 1455.66    69.7 1447.24   139.4 1415.68   159.3 1406.25
   189.2 1390.77   209.1 1381.12   278.8 1348.31   288.8 1343.98   298.7 1340.36
   318.6 1334.13   328.6 1332.02   338.6 1331.26   348.5 1331.54   358.5 1332.24
   388.4 1334.28   398.3  1335.3     458 1345.02   537.7 1361.36   557.6 1365.85
   567.6  1368.5   587.5 1374.53   617.4 1384.04   637.3  1390.7   657.2 1397.76
   677.1 1405.49     697  1413.7     717 1422.44   746.8 1435.91   766.7 1444.24
#Mann= 3 , 0 , 0
       0      .1       0   328.6    .045       0   358.5      .1       0
Bank Sta=328.6,358.5
XS Rating Curve= 0 ,0
Exp/Cntr=0.3,0.1

Type RM Length L Ch R = 1 ,633     ,382.9,388.6,394.3
XS GIS Cut Line= 3
     1946183.434      407866.445     1946137.255      408055.628
     1946052.346      408466.766
#Sta/Elev= 30
       0 1407.48    68.2 1387.52    87.6  1382.5   116.8 1375.54   136.3  1370.4
     146  1367.4   155.8 1363.84   175.3 1355.76   194.7 1349.34   204.7 1346.63
   224.7 1342.29   244.7 1338.81   264.7 1335.98   314.7 1329.65   340.6 1325.54
   344.7 1324.92   354.7  1324.4   355.6 1324.47   364.7 1325.18   374.7 1327.84
   394.6  1334.6   434.6 1347.11   454.6  1353.6   504.6  1370.9   534.6 1381.95
   564.6 1393.68   574.6 1397.81   594.6 1406.73   604.6 1411.62   614.6 1416.97
#Mann= 3 , 0 , 0
       0      .1       0   340.6    .045       0   355.6      .1       0
Bank Sta=340.6,355.6
XS Rating Curve= 0 ,0
Exp/Cntr=0.3,0.1

Type RM Length L Ch R = 1 ,244.4   ,246.2,244.4,242.7
XS GIS Cut Line= 3
     1945930.163       407811.86     1945804.398      407953.146
     1945687.353      408191.715
#Sta/Elev= 30
       0 1397.13      10 1391.87    19.9  1385.5    29.9  1378.7    39.8 1372.36
    49.8 1367.24    59.7 1363.25    89.6  1354.1   119.5 1344.62   129.4 1341.85
   149.3 1336.95   169.2 1332.43   179.2 1330.52   189.2 1329.05   208.8 1327.43
   228.5 1326.31   248.2 1325.57   277.7 1324.77   287.6 1324.26   297.4 1323.39
   307.3 1322.12   324.3 1319.37   326.9 1318.97   336.8 1318.34   339.3 1318.44
   346.6 1318.74   356.5 1320.88   366.3 1324.25   376.2  1327.1   454.9 1347.71
#Mann= 3 , 0 , 0
       0      .1       0   324.3    .045       0   339.3      .1       0
Bank Sta=324.3,339.3
XS Rating Curve= 0 ,0
Exp/Cntr=0.3,0.1

Chan Stop Cuts=-1
Use User Specified Reach Order=0
Composite Channel Slope=5